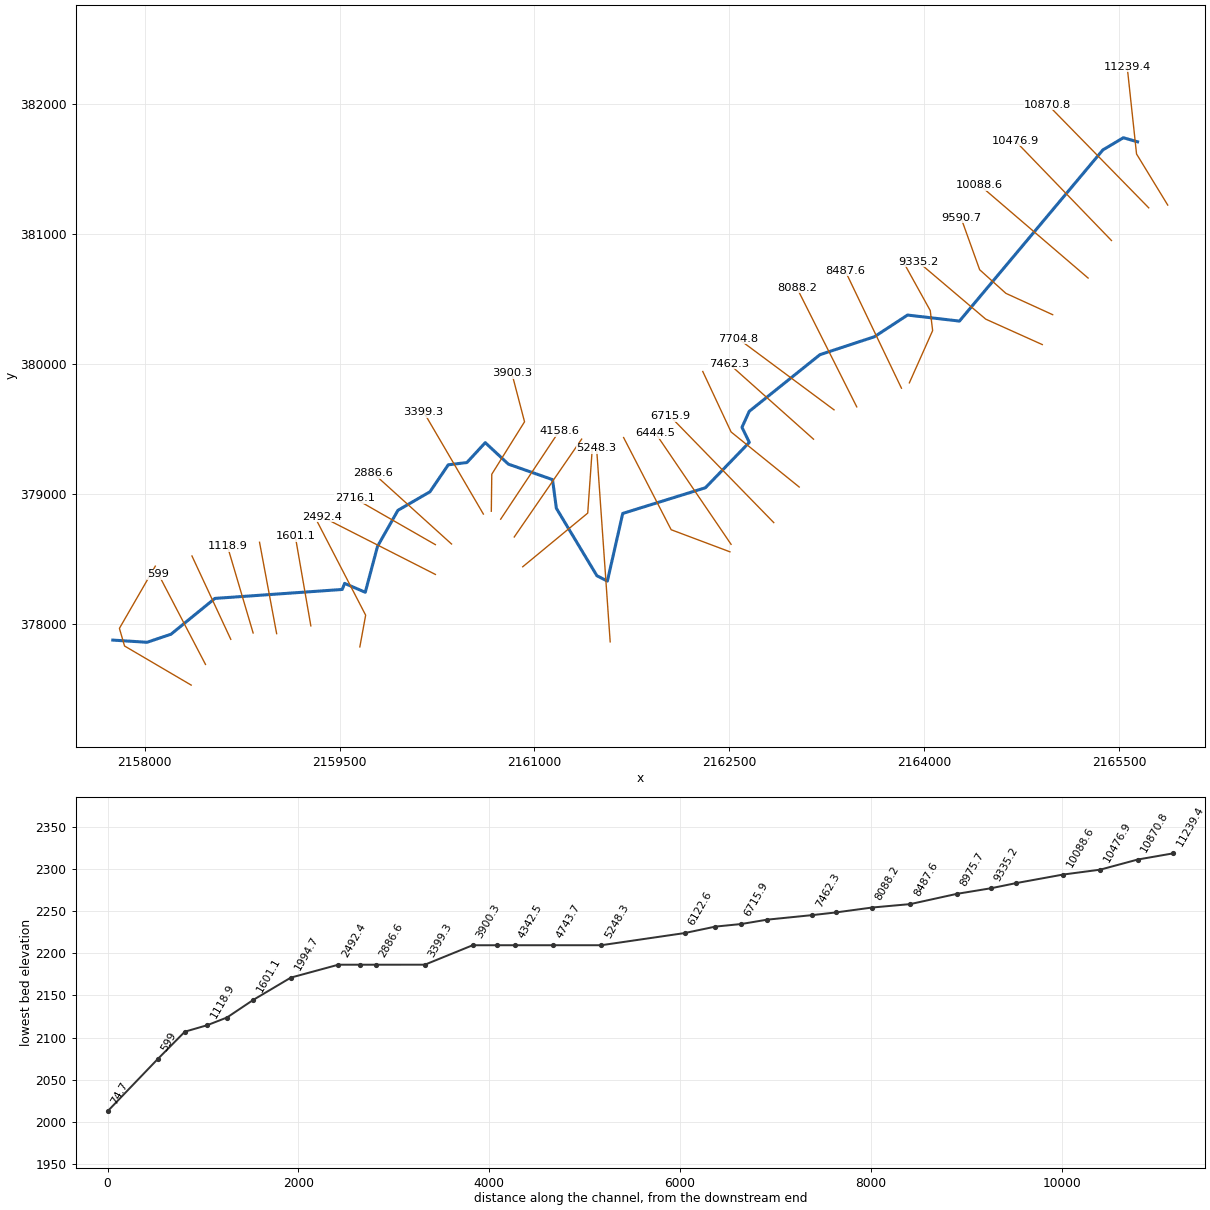
--- SpringCkT3.prj (project) ---

Proj Title=SpringCkT3
Current Plan=p01
Geom File=g01
Flow File=f01
Plan File=p01
DSS Export Rating Curves=0
DSS Export Rating Curve Sorted=0
DSS Export Volume Flow Curves=0
DXF OffsetX=0
DXF OffsetY=0
DXF ScaleX=0
DXF ScaleY=0

--- SpringCkT3.p01 (plan) ---

Plan Title=Floodplain
Program Version=4.00
Geom File=g01
Flow File=f01
K Sum by GR=0
Std Step Tol=0.01
Critical Tol=0.01
Num of Std Step Trials=20
Max Error Tol=0.3
Flow Tol Ratio=0.001
Split Flow NTrial=30
Split Flow Tol=0.02
Split Flow Ratio=0.02
Log Output Level=0
Friction Slope Method=1
Unsteady Friction Slope Method=2
Unsteady Bridges Friction Slope Method=1
Global Log Level=0
CheckData=False
Run HTab=0
Run UNet=0
Run PostProcess=0
UNET Theta=0
UNET Theta Warmup=0
UNET ZTol=0
UNET ZSATol=0
UNET MxIter=0
UNET MaxInSteps=0
UNET DtIC=0
UNET DtMin=0
UNET MaxCRTS=0
UNET WFStab=0
UNET SFStab=0
UNET WFX=0
UNET SFX=0
UNET DSS MLevel=0
UNET DZMax Abort=0
UNET Convert EG Bridges=0
UNET Use Existing IB Tables=0
UNET Froude Limit=0
UNET Froude Power=0
Write IC File=0
Echo Input=False
Echo Output=False
Write Detailed=0

--- SpringCkT3.f01 (steady flow) ---

Flow Title=NFF Regression Equation
Program Version=4.00
Number of Profiles=1
Profile Names=P100yr
River Rch & RM=SpringCkT3,Main      ,11239.4
535.6406
River Rch & RM=SpringCkT3,Main      ,8975.7
584.3071
River Rch & RM=SpringCkT3,Main      ,8487.6
637.8743
River Rch & RM=SpringCkT3,Main      ,6444.5
688.4133
River Rch & RM=SpringCkT3,Main      ,6122.6
858.6764
River Rch & RM=SpringCkT3,Main      ,2886.6
948.6341
River Rch & RM=SpringCkT3,Main      ,74.7
1045.187
Boundary for River Rch & Prof#=SpringCkT3,Main      ,1
Up Type=0
Dn Type=3
Dn Slope=0.089198

--- SpringCkT3.g01 (geometry) ---

Geom Title=USGS 10m DEM
Program Version=4.10

River Reach=SpringCkT3      ,Main
Reach XY= 30
     2165639.246      381709.674     2165529.972      381740.883
     2165372.427      381647.314     2164269.128      380331.331
     2163869.652      380377.622       2163615.1      380210.988
     2163195.959      380072.978     2162651.788      379637.172
     2162596.139       379514.28     2162652.658      379398.924
     2162314.995      379049.957     2161678.871      378852.357
     2161560.702      378332.278     2161480.153      378373.428
     2161168.205      378892.068     2161138.908       379112.36
     2160799.175      379231.344     2160621.173      379396.578
     2160480.181      379243.844     2160336.618      379226.226
     2160195.898       379019.01     2159949.265      378876.107
     2159792.432      378599.187     2159698.282      378246.229
     2159539.345       378314.61     2159520.862      378267.919
     2158541.522      378199.066     2158203.813      377923.795
     2158019.486      377861.771     2157755.962      377878.615

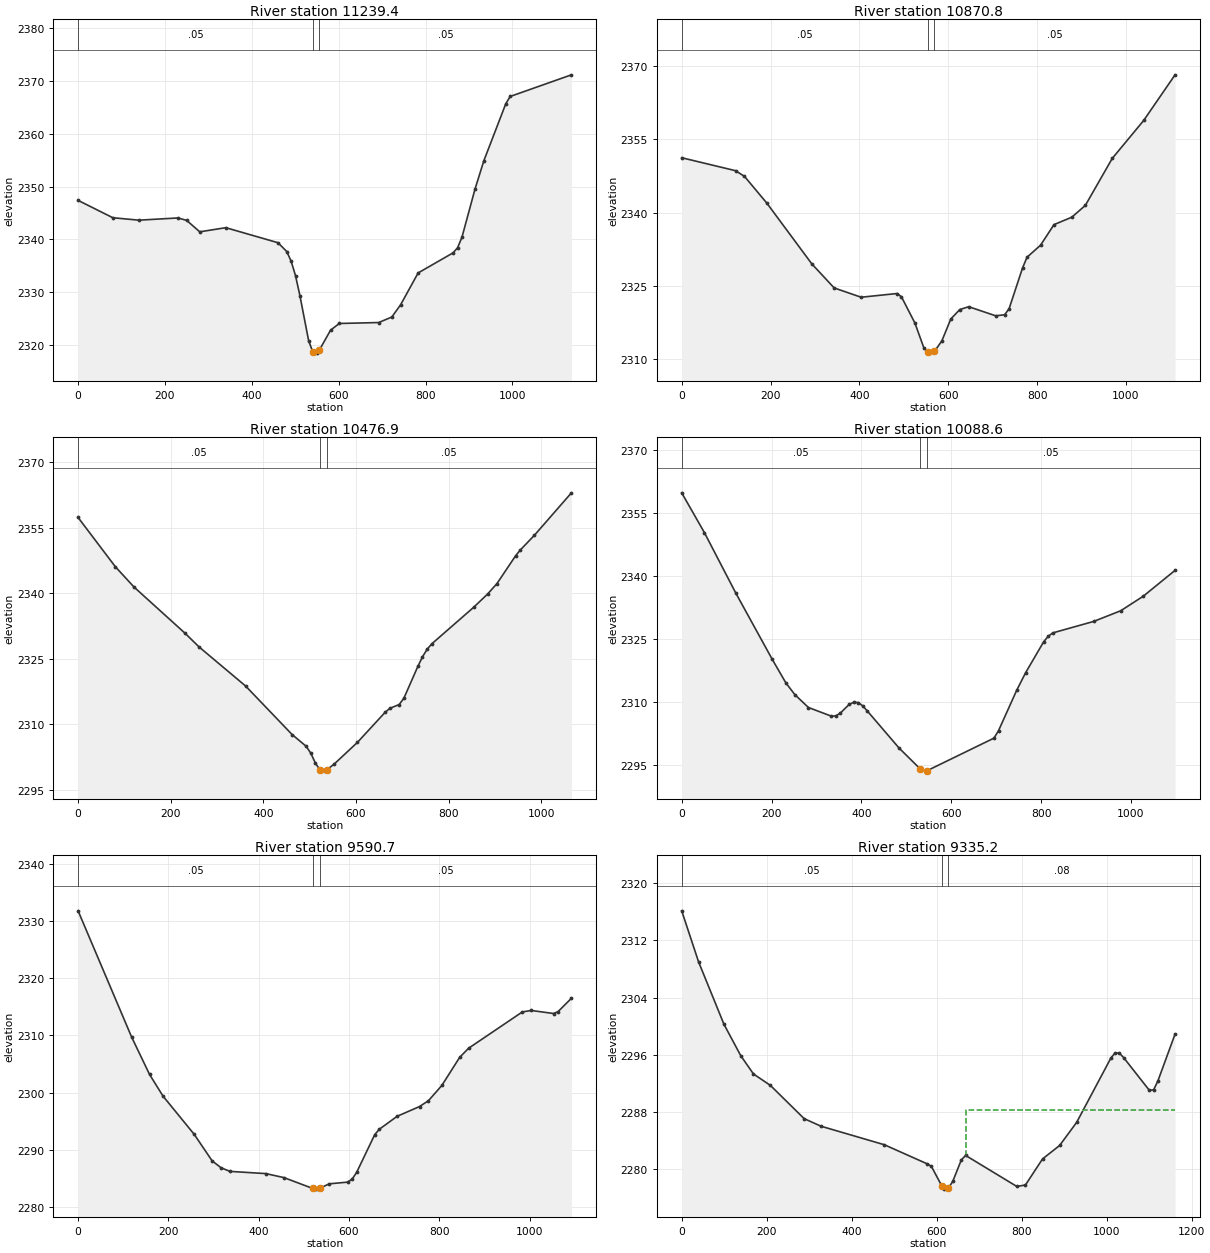
Type RM Length L Ch R = 1 ,11239.4 ,355,368.6,380.3
XS GIS Cut Line= 3
     2165871.258       381223.29     2165631.446       381616.03
     2165559.265      382287.719
#Sta/Elev= 30
       0 2347.39      80 2344.11     140 2343.65   230.1 2344.07   250.1  2343.6
   280.1 2341.45   340.1 2342.23   460.2 2339.39   480.3 2337.73   490.4 2335.92
   500.5 2333.17   510.6 2329.41   530.8 2320.85   540.2 2318.79   550.9 2318.53
   555.2 2319.07   581.2 2322.87   601.3 2324.13   692.1 2324.31   722.3 2325.36
   742.5 2327.67   782.8 2333.68   863.5 2337.49   873.6 2338.44   883.6  2340.4
   913.9 2349.57   934.1 2354.88   984.5 2365.63   994.6 2367.02  1135.7 2371.11
#Mann= 3 , 0 , 0
       0     .05       0   540.2    .045       0   555.2     .05       0
Bank Sta=540.2,555.2
XS Rating Curve= 0 ,0
Exp/Cntr=0.3,0.1

Type RM Length L Ch R = 1 ,10870.8 ,393.2,393.9,394
XS GIS Cut Line= 2
     2165725.146      381201.957     2164948.375      381995.462
#Sta/Elev= 30
       0 2351.25   121.1  2348.6   141.3 2347.44   191.8 2341.94   292.8 2329.53
   343.2  2324.6   403.8  2322.7   484.6 2323.46   494.6 2322.79   524.9 2317.42
   545.1 2312.32   553.8 2311.41   555.2 2311.26   568.8  2311.6   585.5 2313.76
   605.7 2318.25   625.9 2320.18   646.1 2320.76   706.6  2318.9   726.8 2319.11
   736.9 2320.36   767.2 2328.71   777.3  2330.9   807.6 2333.34   837.9 2337.56
   878.2 2339.09   908.5  2341.5   969.1 2351.12  1039.8 2358.88  1110.4 2368.22
#Mann= 3 , 0 , 0
       0     .05       0   553.8    .045       0   568.8     .05       0
Bank Sta=553.8,568.8
XS Rating Curve= 0 ,0
Exp/Cntr=0.3,0.1

Type RM Length L Ch R = 1 ,10476.9 ,386.1,388.3,390.5
XS GIS Cut Line= 2
     2165438.475       380950.71      2164698.27      381716.836
#Sta/Elev= 30
       0  2357.3    80.4 2346.03   120.6 2341.39   231.2 2330.77   261.3 2327.65
   361.8  2318.7   462.3 2307.58   492.4 2304.92   502.5 2303.33   512.6 2301.01
   522.5  2299.5   532.6 2299.22   537.5 2299.55   552.8 2300.82     603 2305.78
   663.3 2312.72   673.4  2313.6   693.4 2314.47   703.5 2315.91   733.6 2323.18
   743.7  2325.4   753.8 2327.14   763.8 2328.37   854.2 2336.73   884.4 2339.78
   904.5 2342.16   944.7 2348.52   954.7 2349.83   984.9 2353.17  1065.3 2362.94
#Mann= 3 , 0 , 0
       0     .05       0   522.5    .045       0   537.5     .05       0
Bank Sta=522.5,537.5
XS Rating Curve= 0 ,0
Exp/Cntr=0.3,0.1

Type RM Length L Ch R = 1 ,10088.6 ,498.4,497.9,497.3
XS GIS Cut Line= 2
     2165258.804      380662.126     2164424.833      381376.461
#Sta/Elev= 30
       0 2359.71    50.4 2350.26   120.9 2335.74   201.5 2320.06   231.7 2314.48
   251.8 2311.66   282.1 2308.59   332.4 2306.56   342.5 2306.58   352.6 2307.21
   372.7 2309.33   382.8 2309.82   392.9 2309.77     403 2308.97     413 2307.78
   483.6 2298.96   530.3 2294.03     544 2293.44   545.3  2293.5   695.1  2301.3
   705.2 2303.08   745.5 2312.66   765.6  2316.9   805.9 2324.28     816 2325.58
   826.1 2326.36   916.8 2329.08   977.2 2331.63  1027.6 2335.11  1098.1 2341.25
#Mann= 3 , 0 , 0
       0     .05       0   530.3    .045       0   545.3     .05       0
Bank Sta=530.3,545.3
XS Rating Curve= 0 ,0
Exp/Cntr=0.3,0.1

Type RM Length L Ch R = 1 ,9590.7  ,254.8,255.5,256.2
XS GIS Cut Line= 4
     2164986.288      380380.436     2164626.266      380544.606
     2164424.654      380726.057     2164280.645      381126.401
#Sta/Elev= 30
       0 2331.76   118.7 2309.69   158.3 2303.18     188 2299.41   257.2 2292.72
   296.8  2288.1   316.6 2286.89   336.3 2286.26   415.8 2285.87     456 2285.17
   519.8 2283.27   526.3 2283.16   534.8 2283.31   556.4 2284.09   596.6 2284.38
   606.6 2284.88   616.7 2286.07   656.9 2292.68   666.9 2293.61   706.5 2295.88
     756 2297.58   775.8  2298.6   805.4 2301.26     845 2306.18   864.8 2307.77
   983.6  2314.1  1003.3 2314.36  1052.8 2313.83  1062.7 2314.15  1092.4 2316.49
#Mann= 3 , 0 , 0
       0     .05       0   519.8    .045       0   534.8     .05       0
Bank Sta=519.8,534.8
XS Rating Curve= 0 ,0
Exp/Cntr=0.3,0.1

Type RM Length L Ch R = 1 ,9335.2  ,376.4,359.5,342.3
XS GIS Cut Line= 3
      2164906.34      380150.612     2164471.417      380346.154
     2163949.709      380788.344
#Sta/Elev= 30
       0 2316.12    39.7 2308.99    99.4 2300.27   139.1 2295.86   168.9 2293.32
   208.6 2291.73   288.1 2287.08   327.8 2286.02   476.9 2283.43   577.4 2280.77
   587.5 2280.41   612.3 2277.64   617.7 2277.23   627.3 2277.34   637.8 2278.32
   657.9 2281.31     668 2281.94   788.6  2277.6   808.8 2277.81     849 2281.45
   889.2 2283.33   929.4 2286.57  1009.9 2295.56    1020 2296.28    1030 2296.23
  1040.1 2295.59  1100.4 2291.03  1110.5 2291.12  1120.5 2292.36  1160.8 2298.89
#Mann= 3 , 0 , 0
       0     .05       0   612.3    .045       0   627.3     .08       0
#XS Ineff= 2 , 0
                          669.34          2288.3
Permanent Ineff=
       F       F
Bank Sta=612.3,627.3
XS Rating Curve= 0 ,0
Exp/Cntr=0.3,0.1

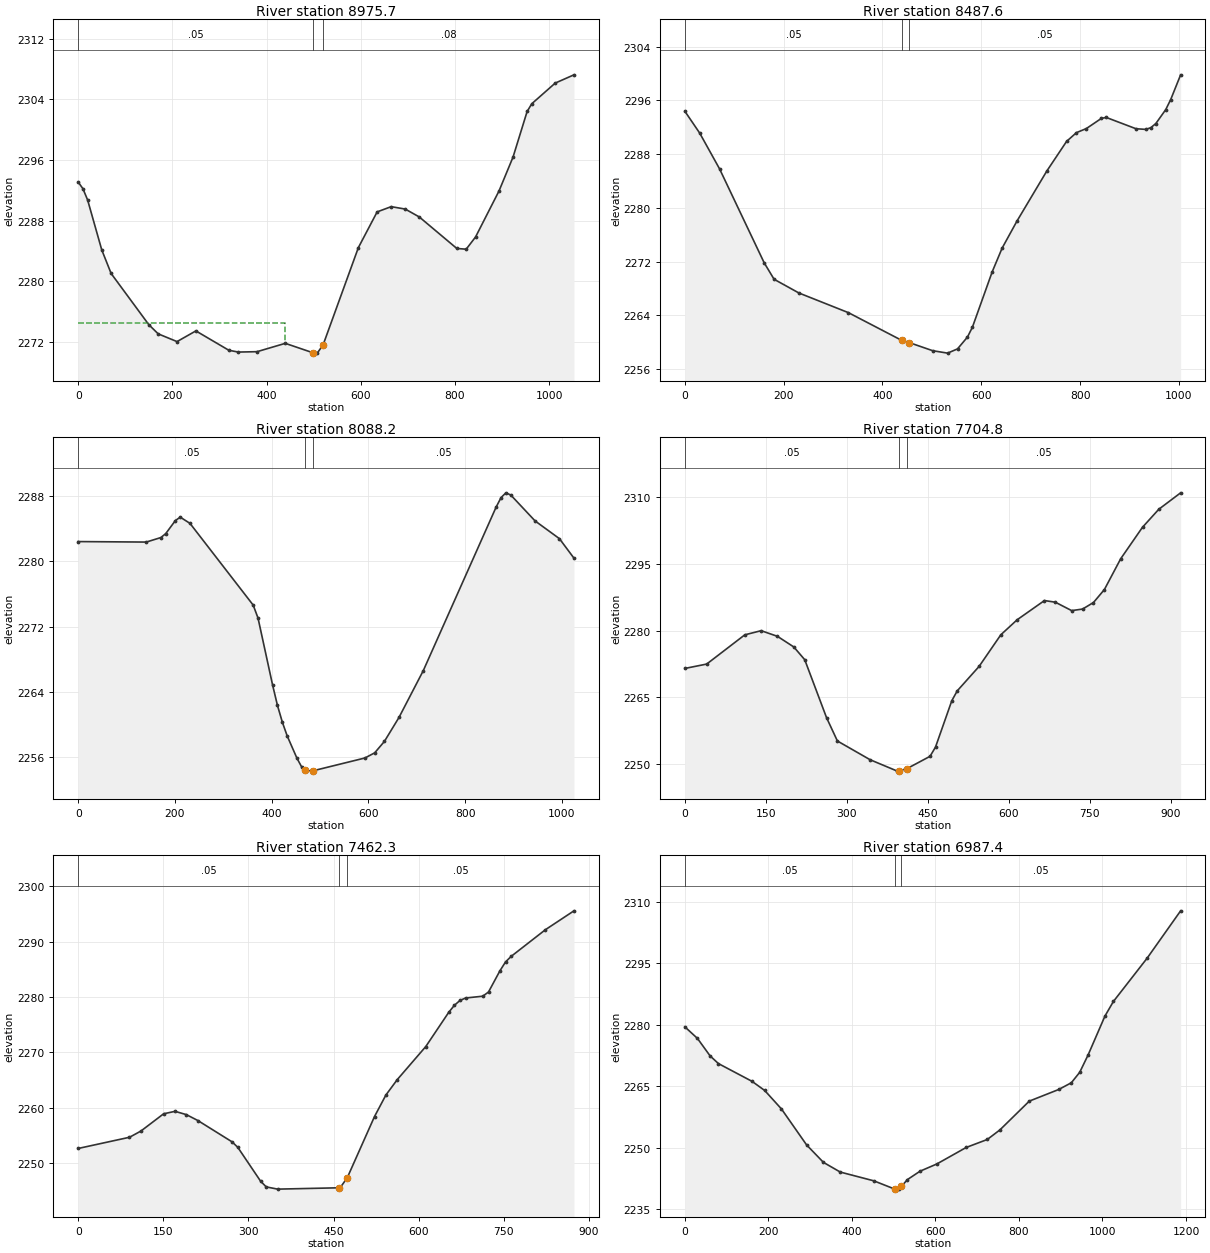
Type RM Length L Ch R = 1 ,8975.7  ,480.9,488.2,495.4
XS GIS Cut Line= 4
     2163883.791       379856.54     2164062.827      380258.016
     2164044.471      380412.118     2163822.698      380812.462
#Sta/Elev= 30
       0 2293.09      10 2292.22      20 2290.73      50 2284.15    69.9 2281.04
   149.9 2274.29   169.8 2273.08   209.8 2272.06   249.8 2273.47   319.7 2270.92
   339.7 2270.68   379.6 2270.73   439.6 2271.83   497.8  2270.6   507.5 2270.54
  519.96 2271.64   594.8 2284.46   634.6 2289.16   664.4 2289.85   694.3 2289.53
   724.1 2288.49   803.7 2284.34   823.6 2284.24   843.5 2285.85   893.3 2291.92
   923.1 2296.39     953  2302.4   962.9 2303.42  1012.6 2306.14  1052.4 2307.23
#Mann= 3 , 0 , 0
       0     .05       0   497.8    .045       0  519.96     .08       0
#XS Ineff= 2 , 0
          439.63 2274.47
Permanent Ineff=
       F       F
Bank Sta=497.8,519.96
XS Rating Curve= 0 ,0
Exp/Cntr=0.3,0.1

Type RM Length L Ch R = 1 ,8487.6  ,394.2,399.4,400.6
XS GIS Cut Line= 2
     2163822.942       379815.29     2163388.921      380720.027
#Sta/Elev= 30
       0 2294.38    30.1 2291.12    70.2 2285.81   160.6 2271.82   180.6 2269.38
   230.8 2267.34   331.1 2264.41   439.4 2260.27   454.4 2259.95   501.7 2258.75
   531.8 2258.39   551.9 2259.02     572 2260.78     582 2262.24   622.1 2270.49
   642.2 2274.02   672.3 2278.05   732.5 2285.47   772.7  2289.9   792.7  2291.2
   812.8 2291.81   842.9 2293.31   852.9 2293.46   913.1 2291.78   933.2 2291.68
   943.2 2291.94   953.3 2292.55   973.4 2294.63   983.4 2296.12  1003.5  2299.8
#Mann= 3 , 0 , 0
       0     .05       0   439.4    .045       0   454.4     .05       0
Bank Sta=439.4,454.4
XS Rating Curve= 0 ,0
Exp/Cntr=0.3,0.1

Type RM Length L Ch R = 1 ,8088.2  ,370.3,383.4,394.2
XS GIS Cut Line= 2
     2163478.977      379671.722     2163018.123        380587.3
#Sta/Elev= 30
       0 2282.43   140.7 2282.37   170.8 2282.92   180.9  2283.4     201 2285.01
     211 2285.42   231.1 2284.66   361.8 2274.65   371.8 2273.06     402 2264.84
     412 2262.36   422.1 2260.31   432.1 2258.63   452.2 2255.91   462.3  2254.8
   469.8 2254.47   482.4 2254.32   484.8 2254.35   592.9 2255.93     613 2256.56
   633.1 2257.96   663.2 2260.89   713.5 2266.63   864.2 2286.67   874.3 2287.82
   884.3  2288.4   894.4 2288.13   944.6 2284.96   994.9 2282.79    1025  2280.4
#Mann= 3 , 0 , 0
       0     .05       0   469.8    .045       0   484.8     .05       0
Bank Sta=469.8,484.8
XS Rating Curve= 0 ,0
Exp/Cntr=0.3,0.1

Type RM Length L Ch R = 1 ,7704.8  ,244.8,242.5,239.6
XS GIS Cut Line= 2
     2163304.267      379648.872     2162566.943      380196.105
#Sta/Elev= 30
       0 2271.52    40.4  2272.5     111 2279.07   141.3    2280   171.5 2278.73
   201.8 2276.34     222 2273.48   262.4 2260.46   282.5 2255.22   343.1 2251.01
   393.5 2248.45   396.5 2248.51   411.5 2249.02   454.1 2251.78   464.2 2253.85
   494.4 2264.27   504.5 2266.49   544.9 2271.97   585.2 2279.08   615.5 2282.46
     666 2286.77   686.1  2286.4   716.4 2284.51   736.6 2284.86   756.8 2286.33
     777 2289.24   807.2 2296.16   847.6 2303.24   877.8 2307.28   918.2 2310.97
#Mann= 3 , 0 , 0
       0     .05       0   396.5    .045       0   411.5     .05       0
Bank Sta=396.5,411.5
XS Rating Curve= 0 ,0
Exp/Cntr=0.3,0.1

Type RM Length L Ch R = 1 ,7462.3  ,473.8,474.9,475.8
XS GIS Cut Line= 2
     2163146.478      379423.414     2162494.218      380004.776
#Sta/Elev= 30
       0 2252.68    90.4  2254.7   110.5 2255.82   150.6 2258.94   170.7 2259.38
   190.8 2258.78   210.9 2257.72   271.2 2253.87   281.2 2252.89   321.4 2246.78
   331.4 2245.74   351.5 2245.34   459.2 2245.58     462 2245.65   474.2  2247.4
   522.2 2258.44   542.3 2262.33   562.4 2265.12   612.6 2271.08   652.8 2277.22
   662.8  2278.5   672.9  2279.4   682.9 2279.84     713 2280.16   723.1 2280.92
   743.2 2284.74   753.2 2286.36   763.3 2287.37   823.5 2292.17   873.7 2295.57
#Mann= 3 , 0 , 0
       0     .05       0   459.2    .045       0   474.2     .05       0
Bank Sta=459.2,474.2
XS Rating Curve= 0 ,0
Exp/Cntr=0.3,0.1

Type RM Length L Ch R = 1 ,6987.4  ,274.1,271.4,268.7
XS GIS Cut Line= 3
     2163036.309      379055.576     2162512.219      379478.942
     2162294.541      379943.903
#Sta/Elev= 30
       0 2279.47    30.2 2276.64    60.3  2272.4    80.4 2270.51   160.9 2266.18
   191.1 2263.96   231.3 2259.45   291.6 2250.67   331.8 2246.43   372.1 2244.07
   452.5 2241.93   502.8 2239.91   503.6 2239.92   512.8 2239.99   518.6 2240.59
     533 2242.24   563.1 2244.28   603.3 2246.04   673.7 2250.07   724.1 2252.01
   754.3 2254.34   824.7 2261.36   895.2  2264.2   925.4 2265.84   945.5 2268.39
   965.7 2272.65  1005.9  2282.1  1026.1 2285.65  1106.6 2296.17  1187.1 2307.75
#Mann= 3 , 0 , 0
       0     .05       0   503.6    .045       0   518.6     .05       0
Bank Sta=503.6,518.6
XS Rating Curve= 0 ,0
Exp/Cntr=0.3,0.1

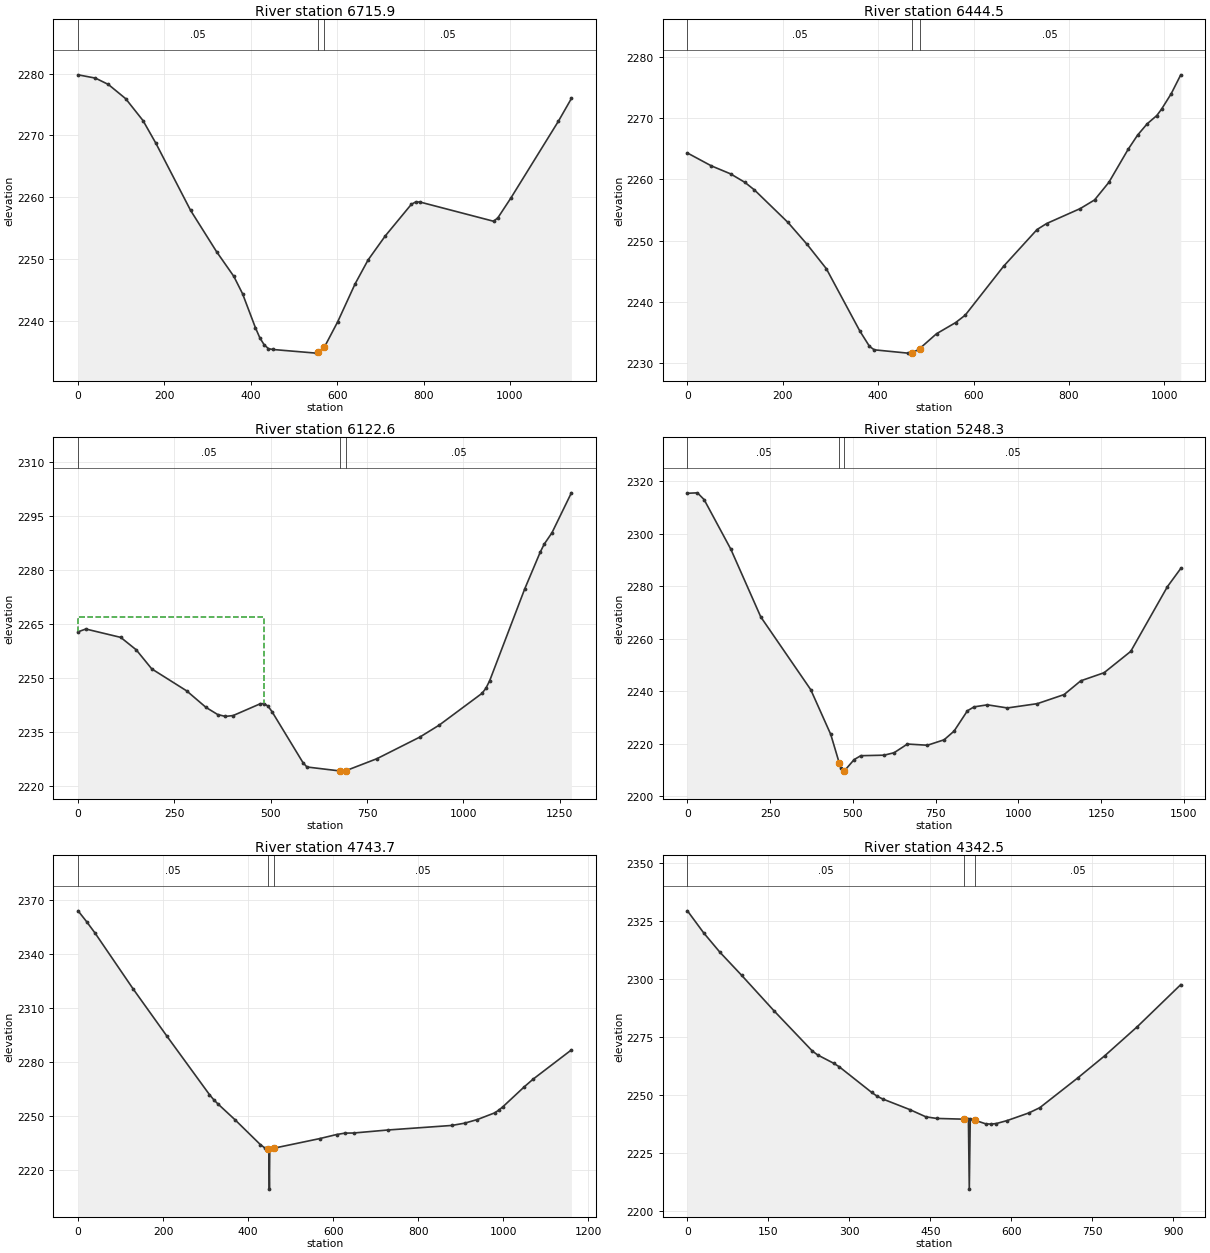
Type RM Length L Ch R = 1 ,6715.9  ,275.4,271.4,267.4
XS GIS Cut Line= 2
     2162840.559       378781.94     2162043.046      379599.802
#Sta/Elev= 30
       0  2279.8    40.1 2279.27    70.1 2278.24   110.2 2275.94   150.3  2272.4
   180.4 2268.69   260.5 2257.86   320.7 2251.17   360.7 2247.17   380.8 2244.37
   410.8 2238.84   420.9 2237.22   430.9  2236.1   440.9 2235.47   450.9 2235.34
   551.1 2234.75   555.4 2234.86   570.4 2235.73   601.2 2239.83   641.3 2245.94
   671.4 2249.82   711.4 2253.73   771.6 2258.83   781.6 2259.22   791.6 2259.21
     962  2256.1     972 2256.65    1002 2259.84  1112.3  2272.3  1142.3 2275.97
#Mann= 3 , 0 , 0
       0     .05       0   555.4    .045       0   570.4     .05       0
Bank Sta=555.4,570.4
XS Rating Curve= 0 ,0
Exp/Cntr=0.3,0.1

Type RM Length L Ch R = 1 ,6444.5  ,322.9,321.9,319.2
XS GIS Cut Line= 2
     2162512.219       378614.89     2161930.425      379470.302
#Sta/Elev= 30
       0 2264.31    50.2 2262.21    90.4 2260.91   120.5 2259.52   140.6 2258.28
   210.9 2252.98   251.1 2249.39   291.3 2245.44   361.6 2235.27   381.7 2232.78
   391.7 2232.21     462 2231.67   471.7  2231.7   486.7 2232.39   522.3 2234.83
   562.4 2236.65   582.5 2237.86   662.9 2245.83   733.2 2251.83   753.3 2252.81
   823.6 2255.24   853.7 2256.65   883.8 2259.53     924 2264.89   944.1 2267.24
   964.2 2269.08   984.3 2270.42   994.3 2271.47  1014.4 2273.97  1034.5 2277.06
#Mann= 3 , 0 , 0
       0     .05       0   471.7    .045       0   486.7     .05       0
Bank Sta=471.7,486.7
XS Rating Curve= 0 ,0
Exp/Cntr=0.3,0.1

Type RM Length L Ch R = 1 ,6122.6  ,888.6,874.4,863.6
XS GIS Cut Line= 3
     2162503.579      378557.287     2162051.392      378727.217
      2161685.61       379435.74
#Sta/Elev= 30
       0  2262.8    20.1 2263.58   110.7 2261.25     151 2257.78   191.2 2252.48
   281.8 2246.36   332.1 2241.75   362.3 2239.77   382.4 2239.24   402.6 2239.49
     473 2242.77   483.1 2242.81   493.2 2242.07   503.2  2240.6     584 2226.33
   594.1 2225.16   680.2 2224.05   684.9 2224.01   695.2 2224.14   775.8 2227.48
   886.8 2233.48   937.3 2236.82  1048.3 2245.66  1058.4 2247.06  1068.5 2249.24
  1159.3 2274.76  1199.7 2285.03  1209.8  2287.2    1230 2290.39  1280.4  2301.5
#Mann= 3 , 0 , 0
       0     .05       0   680.2    .045       0   695.2     .05       0
#XS Ineff= 2 , 0
          481.52  2266.9
Permanent Ineff=
       F       F
Bank Sta=680.2,695.2
XS Rating Curve= 0 ,0
Exp/Cntr=0.3,0.1

Type RM Length L Ch R = 1 ,5248.3  ,526.8,504.5,482.8
XS GIS Cut Line= 2
     2161582.284      377864.965     2161477.877      379351.854
#Sta/Elev= 30
       0 2315.31    30.2 2315.48    50.4  2312.9   130.9 2294.08   221.6 2268.26
   372.6 2240.57   433.1 2223.53   458.6 2212.72   463.3 2210.89   473.4 2209.58
   473.6  2209.6   503.6 2213.96   523.7 2215.45   594.2 2215.65   624.4 2216.58
   664.7 2219.89   725.1 2219.43   775.5  2221.5   805.7 2224.81     846 2232.55
   866.1 2234.03   906.4 2234.81   966.8 2233.62  1057.5 2235.26  1138.1 2238.71
  1188.4 2243.94  1258.9 2247.02  1339.5 2255.15  1450.3 2279.77  1490.6  2286.7
#Mann= 3 , 0 , 0
       0     .05       0   458.6    .045       0   473.6     .05       0
Bank Sta=458.6,473.6
XS Rating Curve= 0 ,0
Exp/Cntr=0.3,0.1

Type RM Length L Ch R = 1 ,4743.7  ,389.1,401.2,409.8
XS GIS Cut Line= 3
     2160909.708      378442.421     2161409.473      378855.025
     2161445.476      379366.255
#Sta/Elev= 30
       0 2364.01    19.9 2358.05    39.9 2351.68   129.6 2320.65   209.4 2294.33
   309.1 2262.02     319 2259.23     329 2256.86   368.9 2248.14   428.7 2234.32
   438.7 2232.55   446.5 2232.07   448.7 2231.93  450.08 2209.57  451.01 2231.94
   461.5 2232.33   568.3  2237.6   608.2 2239.87   628.1 2240.66   648.1 2240.71
   728.5 2242.38   879.2 2244.91   909.4 2246.17   939.5  2248.2   979.7 2251.85
   989.7  2253.4   999.8 2255.36    1050  2266.4  1070.1 2270.52  1160.6 2286.82
#Mann= 3 , 0 , 0
       0     .05       0   446.5    .045       0   461.5     .05       0
Bank Sta=446.5,461.5
XS Rating Curve= 0 ,0
Exp/Cntr=0.3,0.1

Type RM Length L Ch R = 1 ,4342.5  ,188.8,183.9,182.5
XS GIS Cut Line= 2
      2160844.24      378671.414     2161362.671      379423.859
#Sta/Elev= 30
       0 2329.48    30.1 2319.97    60.2 2311.63   100.4  2301.7   160.7 2286.32
     231 2269.16     241 2267.41   271.1 2263.77   281.2 2262.29   341.4 2251.22
   351.4  2249.6   361.5 2248.43   411.7 2243.86   441.8 2240.71   461.9 2240.03
   512.1 2239.71  520.49 2239.64   522.1 2209.57  523.87  2239.6   532.2 2239.28
   552.3 2237.72   562.3 2237.59   572.4 2237.84   592.4 2239.12   632.6 2242.42
   652.7 2244.66     723 2257.48   773.2 2267.07   833.4 2279.58   913.8 2297.68
#Mann= 3 , 0 , 0
       0     .05       0   512.1    .045       0   532.2     .05       0
Bank Sta=512.1,532.2
XS Rating Curve= 0 ,0
Exp/Cntr=0.3,0.1

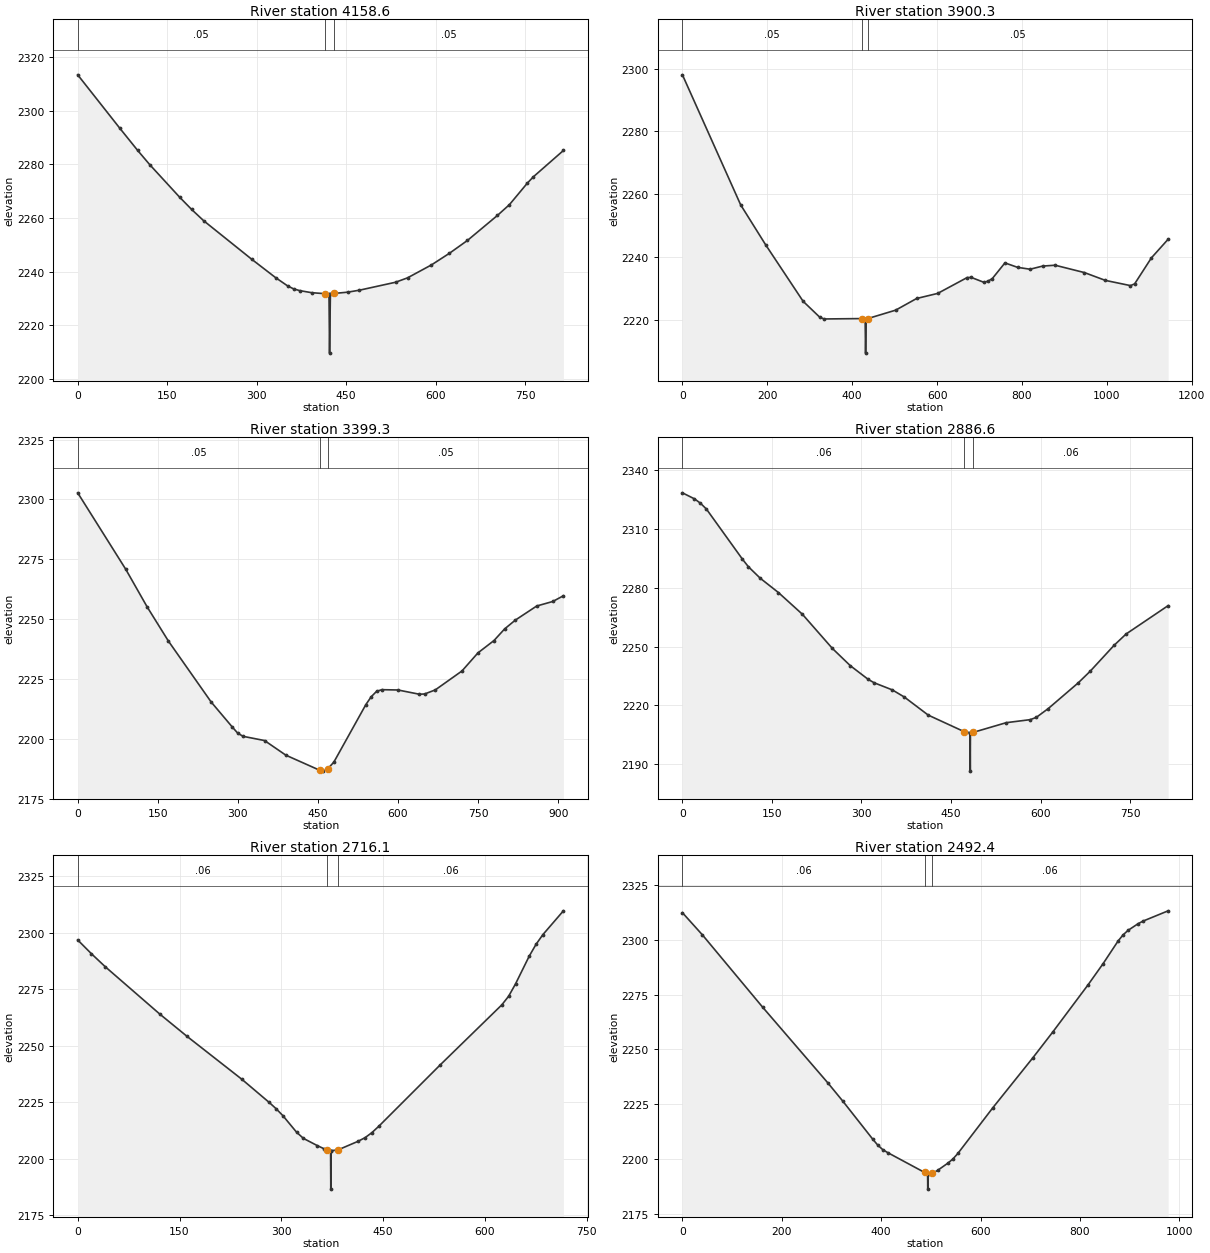
Type RM Length L Ch R = 1 ,4158.6  ,257.6,258.3,259
XS GIS Cut Line= 2
     2160739.833      378808.222     2161190.862       379486.28
#Sta/Elev= 30
       0 2313.46    70.4 2293.58   100.5 2285.25   120.6 2279.97   170.9 2267.78
     191 2263.21   211.1 2259.01   291.6 2244.64   331.8 2237.75   351.9 2234.67
   361.9 2233.56     372 2232.91   392.1 2232.13  414.13 2231.76  421.35 2231.74
   422.3 2209.56  423.72 2231.74  430.27 2231.85   452.4 2232.31   472.5 2233.06
   532.9 2236.02     553 2237.66   593.2  2242.5   623.3 2246.83   653.5 2251.63
   703.8 2260.97   723.9 2264.99     754 2273.04   764.1  2275.4   814.4 2285.21
#Mann= 3 , 0 , 0
       0     .05       0  414.13    .045       0  430.27     .05       0
Bank Sta=414.13,430.27
XS Rating Curve= 0 ,0
Exp/Cntr=0.3,0.1

Type RM Length L Ch R = 1 ,3900.3  ,474.1,501,526.7
XS GIS Cut Line= 4
     2160667.829      378869.426     2160671.429      379153.843
     2160923.444      379557.067      2160825.96      379928.948
#Sta/Elev= 30
       0    2298   137.3 2256.65   196.2 2243.95   284.4 2226.01   324.1 2220.89
     334  2220.4   422.2 2220.52  430.47 2220.51  431.54 2209.54     433 2220.51
   437.2 2220.54   502.4  2223.2   551.9 2226.91   601.4 2228.52   670.8 2233.56
   680.7  2233.6   710.4 2232.04   720.3 2232.43   730.2 2233.25   759.9 2238.22
   789.5 2236.81   819.1 2236.21   848.7 2237.21   878.2 2237.48   947.2 2235.14
   996.5 2232.66  1055.7    2231  1065.5 2231.56    1105 2239.82  1144.4 2245.74
#Mann= 3 , 0 , 0
       0     .05       0   422.2    .045       0   437.2     .05       0
Bank Sta=422.2,437.2
XS Rating Curve= 0 ,0
Exp/Cntr=0.3,0.1

Type RM Length L Ch R = 1 ,3399.3  ,505.8,512.7,518.7
XS GIS Cut Line= 2
     2160606.625      378847.824     2160147.002      379632.839
#Sta/Elev= 30
       0 2302.74      90  2270.8     130 2255.11   169.9  2240.8   249.9 2215.37
   289.9  2204.8   299.9 2202.29   309.9    2201   349.9 2199.25   389.9 2193.13
   452.9 2186.87   459.8 2186.47   467.9 2187.32   479.8 2190.25   539.8  2214.3
   549.8 2217.56   559.8 2219.81   569.8  2220.5   599.8 2220.37   639.8  2218.6
   649.8  2218.7   669.8 2220.41   719.7 2228.31   749.7 2235.88   779.7 2241.03
   799.7  2245.9   819.7 2249.57   859.7 2255.45   889.7 2257.34   909.7 2259.73
#Mann= 3 , 0 , 0
       0     .05       0   452.9    .045       0   467.9     .05       0
Bank Sta=452.9,467.9
XS Rating Curve= 0 ,0
Exp/Cntr=0.3,0.1

Type RM Length L Ch R = 1 ,2886.6  ,165.6,170.5,175.4
XS GIS Cut Line= 2
     2160361.811       378617.41     2159758.172      379163.252
#Sta/Elev= 30
       0 2328.44    20.1 2325.38    30.1 2323.17    40.2 2320.16   100.5 2294.61
   110.5 2290.74   130.6 2284.81   160.8 2277.58     201 2266.49   251.2 2249.07
   281.3 2240.25   311.5 2233.22   321.5  2231.5   351.7  2227.9   371.8 2224.26
   411.9 2215.03   472.4 2206.55  481.88 2206.09   482.3 2186.46  482.56 2206.08
   487.4 2206.25   542.6 2211.18   582.7 2212.72   592.8 2213.86   612.9 2218.36
   663.1 2231.47   683.2 2237.41   723.4 2250.69   743.5 2256.45   813.8 2270.89
#Mann= 3 , 0 , 0
       0     .06       0   472.4    .045       0   487.4     .06       0
Bank Sta=472.4,487.4
XS Rating Curve= 0 ,0
Exp/Cntr=0.3,0.1

Type RM Length L Ch R = 1 ,2716.1  ,222.6,223.7,224.9
XS GIS Cut Line= 2
     2160237.334      378612.598     2159616.585      378968.271
#Sta/Elev= 30
       0 2296.81    20.2 2290.71    40.3 2285.02   120.9 2263.98   161.2 2254.07
   241.8  2235.1   282.1 2224.84   292.2 2222.08   302.3 2218.96   322.4 2211.65
   332.5 2208.92   352.7 2205.76   362.8 2204.34   367.9 2203.91  372.47 2203.53
   372.8 2186.45  373.11 2203.51   382.9 2203.76   413.1 2207.65   423.2 2209.23
   433.3 2211.46   443.4 2214.27     534 2241.49   624.7 2268.07   634.8 2271.92
   644.9 2277.36     665 2289.61   675.1 2294.88   685.2 2299.18   715.4 2309.71
#Mann= 3 , 0 , 0
       0     .06       0   367.9    .045       0   382.9     .06       0
Bank Sta=367.9,382.9
XS Rating Curve= 0 ,0
Exp/Cntr=0.3,0.1

Type RM Length L Ch R = 1 ,2492.4  ,505.6,497.7,485.8
XS GIS Cut Line= 2
     2160237.603      378383.396     2159366.351      378826.223
#Sta/Elev= 30
       0 2312.27    40.3 2302.15   161.2 2269.31   292.2 2234.91   322.4 2226.58
   382.9 2209.19     393 2206.48     403 2204.43   413.1 2203.05   487.2 2194.04
  493.31  2193.5   493.7 2186.44  493.92 2193.48   502.2 2193.66   503.8  2193.7
   513.8 2195.03     534 2198.25   544.1 2200.13   554.2 2202.67   624.7 2223.52
   705.3 2246.28   745.6 2258.08   816.1 2279.41   846.4 2289.06   876.6 2299.38
   886.6 2302.16   896.7 2304.24   916.9 2307.26     927 2308.46   977.3 2313.12
#Mann= 3 , 0 , 0
       0     .06       0   487.2    .045       0   502.2     .06       0
Bank Sta=487.2,502.2
XS Rating Curve= 0 ,0
Exp/Cntr=0.3,0.1

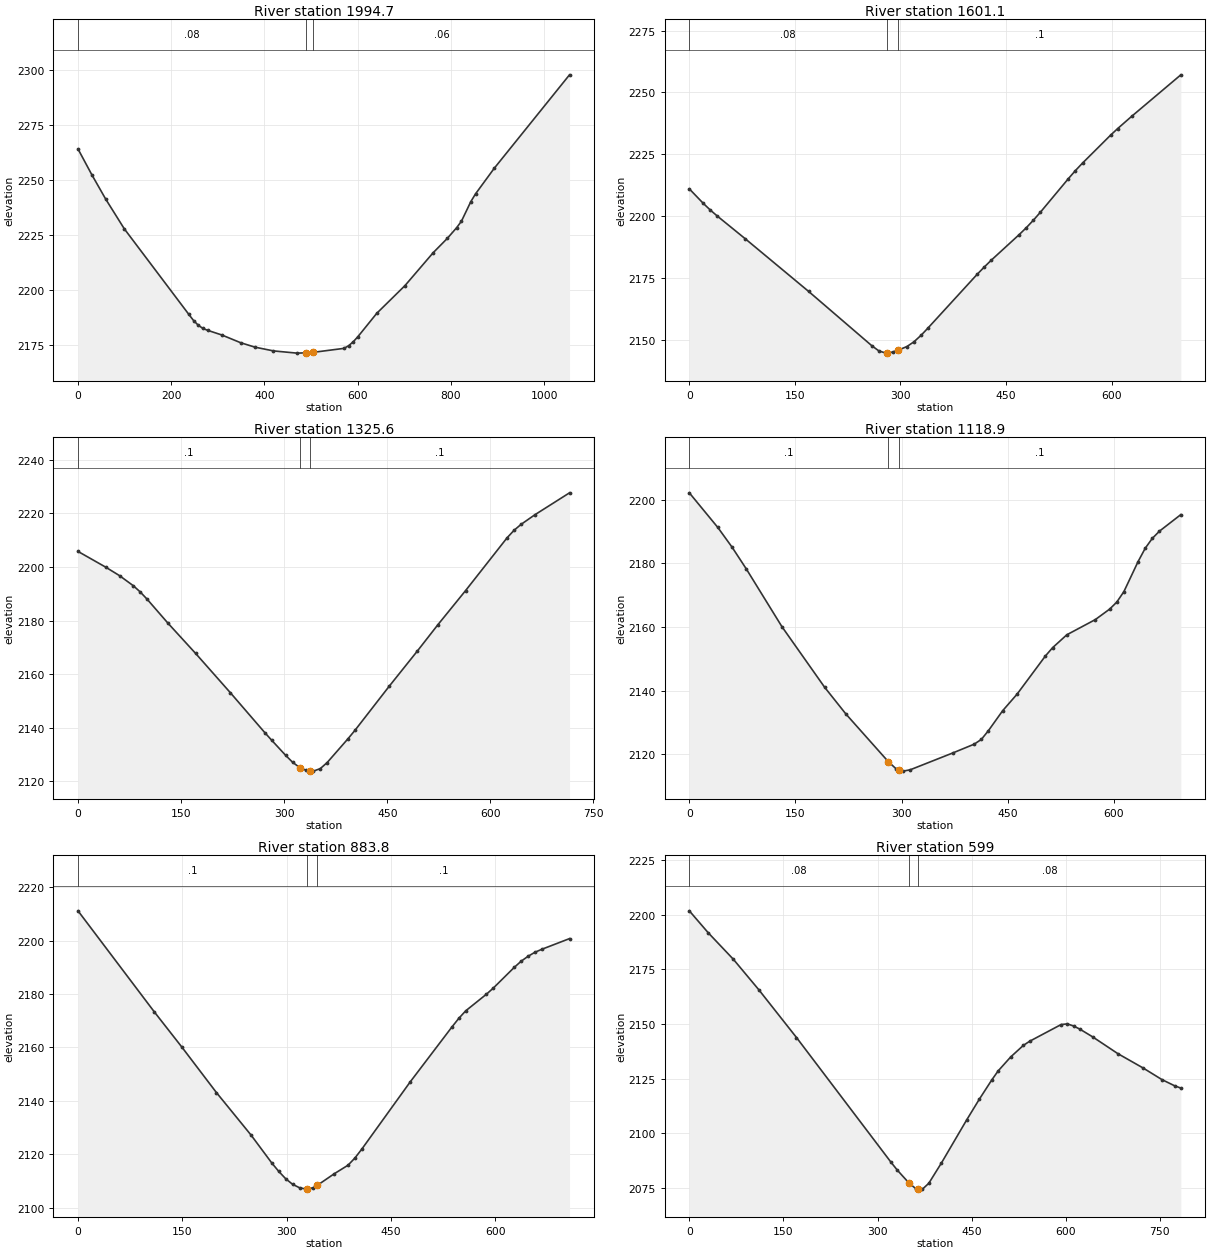
Type RM Length L Ch R = 1 ,1994.7  ,400.6,393.6,377.3
XS GIS Cut Line= 3
     2159656.478      377826.275     2159701.171      378070.178
     2159330.349      378786.621
#Sta/Elev= 30
       0 2263.95    29.8 2252.17    59.5 2241.13    99.2 2227.69     238 2188.69
     248 2185.95     258 2183.83   268.1 2182.36   278.2  2181.5   308.5 2179.39
   348.8 2175.88   379.1 2173.88   419.4 2172.14   469.8 2171.13   490.2 2171.26
   505.2  2171.5   570.6 2173.29   580.7 2174.48   590.8 2176.33   600.9 2178.68
   641.2 2189.25   701.7 2201.84   762.2 2216.79   792.5 2223.29   812.7  2228.2
   822.8  2231.1   842.9 2239.98     853 2243.52   893.3 2255.19  1054.7 2297.64
#Mann= 3 , 0 , 0
       0     .08       0   490.2    .045       0   505.2     .06       0
Bank Sta=490.2,505.2
XS Rating Curve= 0 ,0
Exp/Cntr=0.3,0.1

Type RM Length L Ch R = 1 ,1601.1  ,275.2,275.5,275.7
XS GIS Cut Line= 2
     2159279.612      377987.789     2159159.972      378675.719
#Sta/Elev= 30
       0 2211.06      20 2205.15    29.9 2202.49    39.9 2200.04    79.8 2190.82
   169.6  2169.6   259.4 2147.65   269.3 2145.59   279.3 2144.69     281 2144.76
   289.3 2145.13     296  2145.8   309.2 2147.36   319.2 2149.28   329.2 2151.88
   339.2 2154.87     409 2176.55     419 2179.47   428.9 2182.22   468.8 2192.62
   478.8 2195.38   488.8  2198.4   498.8 2201.63   538.6 2215.21   548.6 2218.47
   558.6 2221.47   598.5 2232.76   608.5 2235.41   628.4 2240.36   698.3 2257.14
#Mann= 3 , 0 , 0
       0     .08       0     281    .045       0     296      .1       0
Bank Sta=281,296
XS Rating Curve= 0 ,0
Exp/Cntr=0.3,0.1

Type RM Length L Ch R = 1 ,1325.6  ,204.4,206.7,209.1
XS GIS Cut Line= 2
     2159016.404      377927.969       2158884.8      378630.854
#Sta/Elev= 30
       0 2205.81    40.3 2199.94    60.4 2196.77    80.6 2192.98    90.6 2190.67
   100.7 2187.94   130.9 2179.02   171.2 2167.72   221.6 2153.09   271.9 2138.14
     282 2135.28   302.2 2129.67   312.2 2127.12   322.6 2125.13   332.4 2124.06
   337.6 2123.92   342.4  2123.8   352.5 2124.73   362.6 2127.02   392.8 2135.88
   402.9 2139.01   453.2 2155.62   493.5 2168.55   523.7 2178.48     564 2191.22
   624.4 2210.93   634.5 2213.71   644.6  2215.9   664.7 2219.49   715.1 2227.68
#Mann= 3 , 0 , 0
       0      .1       0   322.6    .045       0   337.6      .1       0
Bank Sta=322.6,337.6
XS Rating Curve= 0 ,0
Exp/Cntr=0.3,0.1

Type RM Length L Ch R = 1 ,1118.9  ,231.7,235.1,238.5
XS GIS Cut Line= 2
       2158835.5      377933.392     2158638.357        378599.3
#Sta/Elev= 30
       0 2202.13    40.3 2191.24    60.4 2185.05    80.5 2178.22   130.8 2160.09
   191.2 2141.03   221.4 2132.59     281  2117.7   291.9 2115.46     296 2115.14
     302 2114.68     312 2115.09   372.4  2120.4   402.6 2123.16   412.7 2124.66
   422.7 2127.42   442.8 2133.68     463 2138.84   503.2 2150.88   513.3 2153.47
   533.4 2157.52   573.7  2162.3   593.8 2165.57   603.9 2167.77     614 2171.07
   634.1 2180.53   644.2 2184.72   654.2 2187.82   664.3 2190.09   694.5 2195.29
#Mann= 3 , 0 , 0
       0      .1       0     281    .045       0     296      .1       0
Bank Sta=281,296
XS Rating Curve= 0 ,0
Exp/Cntr=0.3,0.1

Type RM Length L Ch R = 1 ,883.8   ,283.8,284.7,285.3
XS GIS Cut Line= 2
      2158663.65      377884.475     2158365.019      378525.357
#Sta/Elev= 30
       0 2211.13   109.5  2173.4   149.4 2160.13   199.2 2143.08     249 2127.17
   278.8 2116.73   288.8 2113.59   298.8 2110.84   308.7 2108.76   318.7 2107.47
   328.6 2106.96   329.4    2107   338.6  2107.5   344.4 2108.41   368.5  2112.7
   388.4 2115.91   398.3  2118.6   408.3 2121.96     478 2147.15   537.8 2167.63
   547.7 2170.87   557.7  2173.7   587.5 2179.92   597.5 2182.24   627.4 2189.93
   637.3 2192.24   647.3  2194.1   657.2 2195.61   667.2 2196.74     707 2200.73
#Mann= 3 , 0 , 0
       0      .1       0   329.4    .045       0   344.4      .1       0
Bank Sta=329.4,344.4
XS Rating Curve= 0 ,0
Exp/Cntr=0.3,0.1

Type RM Length L Ch R = 1 ,599     ,528.2,524.4,520.1
XS GIS Cut Line= 2
     2158469.036      377691.589     2158106.653      378386.157
#Sta/Elev= 30
       0 2201.71    30.1 2191.68    70.3 2179.51   110.5  2165.7   170.8 2143.77
   321.4 2086.74   331.4 2083.14   350.1 2077.22   361.6 2074.49   365.1 2074.47
   371.6 2074.42   381.7 2077.09   401.8 2086.37   441.9    2106     462 2115.45
   482.1 2124.37   492.2 2128.48   512.2 2134.87   532.3 2140.14   542.4 2142.05
   592.6  2149.7   602.6    2150   612.7    2149   622.7 2147.56   642.8 2144.07
     683 2136.39   723.2 2129.84   753.3 2124.51   773.4  2121.7   783.4 2120.63
#Mann= 3 , 0 , 0
       0     .08       0   350.1    .045       0   365.1     .08       0
Bank Sta=350.1,365.1
XS Rating Curve= 0 ,0
Exp/Cntr=0.3,0.1

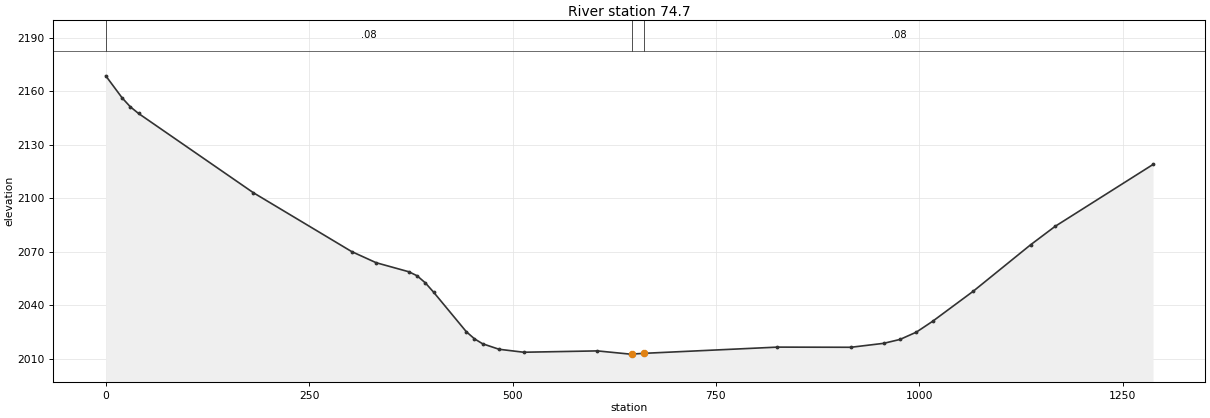
Type RM Length L Ch R = 1 ,74.7    ,77.6,74.7,71.9
XS GIS Cut Line= 4
     2158358.933      377532.671      2157846.36      377833.315
     2157806.931      377968.851     2158082.932      378446.924
#Sta/Elev= 30
       0 2168.59    20.1 2156.23    30.2 2151.21    40.3 2147.49   181.3  2103.1
   302.2 2070.08   332.4 2063.82   372.7 2058.73   382.7  2056.5   392.8 2052.55
   402.9 2047.36   443.2 2025.15   453.2 2021.17   463.3 2018.37   483.4 2015.31
   513.7 2013.64   604.3 2014.39   644.6 2012.58   646.8 2012.61   661.8 2013.03
   825.7 2016.51     916 2016.42   956.2 2018.63   976.3 2020.81   996.4  2024.9
  1016.4 2030.98  1066.6 2047.92  1136.9 2073.88    1167  2084.2  1287.4 2118.91
#Mann= 3 , 0 , 0
       0     .08       0   646.8    .045       0   661.8     .08       0
Bank Sta=646.8,661.8
XS Rating Curve= 0 ,0
Exp/Cntr=0.3,0.1
Stream Node=SpringCkT3      ,Main            , 0 , 0 ,Upstream end
Stream Node=SpringCkT3      ,Main            , 0 , 1 ,Downstream end

Chan Stop Cuts=-1
Use User Specified Reach Order=0
Composite Channel Slope=5